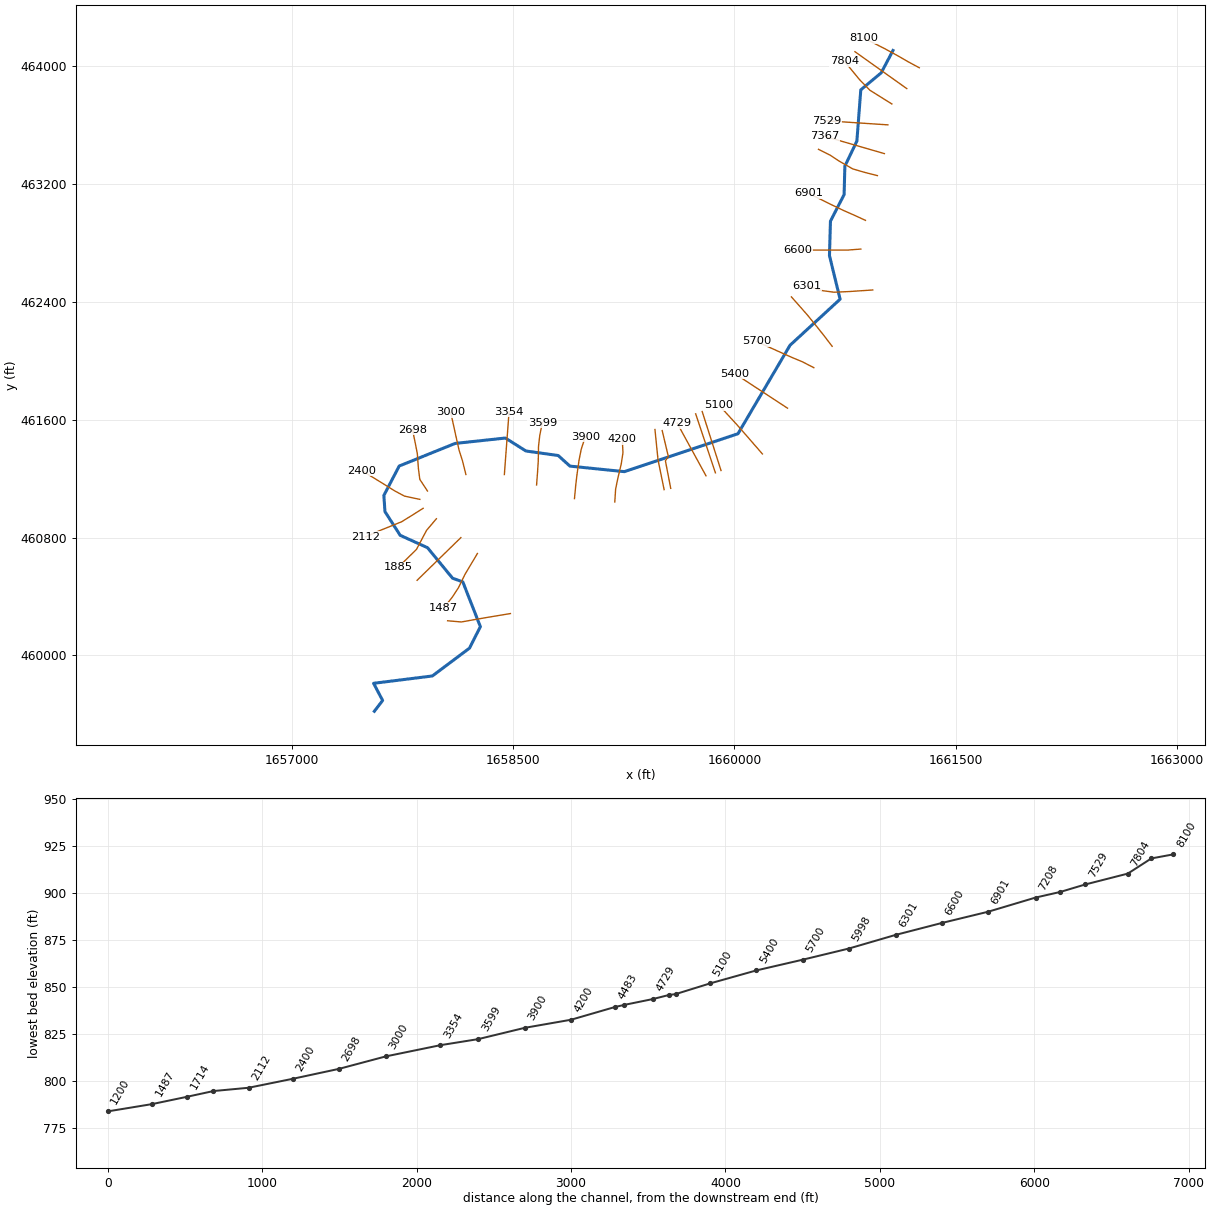
--- CedrRn.prj (project) ---

Proj Title=CedrRn
Current Plan=p01
Default Exp/Contr=0,0
English Units
Geom File=g01
Flow File=f01
Plan File=p01
BEGIN DESCRIPTION:
---------- MODELED AS PART OF WVEM CTP PROGRAM, 2025----------
Stream Name: Cedar Run
Flood Zone: AFH
Marshall County, WV
HEC-RAS Version: RAS 6.6
Vertical Datum: NAVD88
Projection: NAD 1983 StatePlane West Virginia N FIPS 4701 (US Feet)
Terrain: 1-meter West Virginia FEMA R3 South Central (collected 2018-2019)
Land Use: 2024 NLCD
Hydrologic Method:
Duda et al., "Estimation of magnitude and frequency of floods for rural, unregulated streams in and near Virginia and West Virginia." September 8, 2025.
Additional Model Notes:
None
END DESCRIPTION:
DSS Export Rating Curves= 0
DSS Export Rating Curve Sorted= 0
DSS Export Volume Flow Curves= 0
DXF OffsetX= 0
DXF OffsetY= 0
DXF ScaleX= 0
DXF ScaleY= 0

--- CedrRn.p01 (plan) ---

Plan Title=Floodplain
Program Version=6.60
Short Identifier=Floodplain
Geom File=g01
Flow File=f01
Subcritical Flow
K Sum by GR= 0
Std Step Tol= 0.01
Critical Tol= 0.01
Num of Std Step Trials= 20
Max Error Tol= 0.3
Flow Tol Ratio= 0.001
Split Flow NTrial= 30
Split Flow Tol= 0.02
Split Flow Ratio= 0.02
Log Output Level= 0
Friction Slope Method= 1
Unsteady Friction Slope Method= 2
Unsteady Bridges Friction Slope Method= 1
Parabolic Critical Depth
Global Vel Dist= 0 , 0 , 0
Global Log Level= 0
CheckData=False
Encroach Param=-1 ,0,0, 0
Flow Ratio Tolerance=0.1
Flow Ratio Min Ratio=0.5
Flow Ratio Max Ratio=4
Flow Ratio Max Iterations= 10
Mapping Interval=1HOUR
Computation Time Step Use Courant=        0
Computation Time Step Use Time Series=    0
Computation Time Step Count To Double=0
Computation Time Step Max Doubling=0
Computation Time Step Max Halving=0
Computation Time Step Residence Courant=0
Run HTab= 0
Run UNet= 0
Run Sediment= 0
Run PostProcess= 0
Run WQNet= 0
Run RASMapper=-1
UNET Theta= 0
UNET Theta Warmup= 0
UNET ZTol= 0
UNET ZSATol= 0
UNET MxIter= 0
UNET Max Iter WO Improvement= 0
UNET MaxInSteps= 0
UNET DtIC= 0
UNET DtMin= 0
UNET MaxCRTS= 0
UNET WFStab= 0
UNET SFStab= 0
UNET WFX= 1
UNET SFX= 1
UNET Gravity=32.17405
UNET 1D Methodology=Finite Difference
UNET DSS MLevel= 1
UNET Pardiso=0
UNET DZMax Abort= 0
UNET Use Existing IB Tables= 0
UNET Froude Reduction=False
UNET Froude Limit= 0
UNET Froude Power= 0
UNET D1 Cores= 0
UNET WindReference=Eulerian
UNET WindDragFormulation=Hsu (1988)
UNET D2 Coriolis=0
UNET D2 Cores= 0
UNET D2 Theta= 1
UNET D2 Theta Warmup= 1
UNET D2 Z Tol= 0.01
UNET D2 Volume Tol= 0.01
UNET D2 Max Iterations= 20
UNET D2 Advanced Convergence=0
UNET D2 WS Max Tol=0.15
UNET D2 WS RMS Tol=0.002
UNET D2 WS Stall Tol=1
UNET D2 Equation= 0
UNET D2 RampUpFraction=0.1
UNET D2 TimeSlices= 1
UNET D2 Turbulence Formulation=Non-Conservative (original)
UNET D2 Eddy Viscosity=0.3
UNET D2 Transverse Eddy Viscosity=0.1
UNET D2 Smagorinsky Mixing=0
UNET D2 BCVolumeCheck=0
UNET D2 Cores=0
UNET D2 SolverType=PARDISO (Direct)
UNET D2 Minimum Iterations= 3
UNET D2 Maximum Iterations= 30
UNET D2 Restart Number= 10
UNET D2 Relaxation Coeff=1.3
UNET D2 SOR Precondition Iterations= 10
UNET D2 ILUT Maximum Fill= 8
UNET D2 ILUT Tolerance=1E-08
UNET D2 Convergence Tolerance=0.00001
PS Theta= 1
PS WS Tol= 0.01
PS Volume Tol= 0.01
PS Max Iterations= 20
PS Equation= 0
PS Advance Time Step=-1
PS Target Courant=0.9
PS Time Slices= 1
PS Iterate With 2D=0
PS Project Initial WSE from DS=-1
PS Ramp Up Initial WSE from US=-1
PS Cores=0
UNET D1D2 MaxIter= 0
UNET D1D2 ZTol=0.01
UNET D1D2 QTol=0.1
UNET D1D2 MinQTol=1
Write IC File= 0
Write IC File at Fixed DateTime=0
Write IC File at Sim End=0
Echo Input=False
Echo Parameters=False
Echo Output=False
Write Detailed= 0
HDF Write Warmup=0
HDF Write Time Slices=0
HDF Flush=0
HDF Compression= 1
HDF Chunk Size= 1
HDF Spatial Parts= 1
HDF Use Max Rows=0
HDF Fixed Rows= 1
Calibration Method= 0
Calibration Iterations= 20
Calibration Max Change=0.05
Calibration Tolerance=0.2
Calibration Maximum=1.5
Calibration Minimum=0.5
Calibration Optimization Method= 1
WQ AD Non Conservative
WQ ULTIMATE=-1
WQ Max Comp Step=1HOUR
WQ Output Interval=15MIN
WQ Output Selected Increments= 0
WQ Create Restart=0
WQ Fixed Restart=0
WQ System Summary=0
WQ Write To DSS=0
Sorting and Armoring Iterations= 10
XS Update Threshold= 0.02
Bed Roughness Predictor= 0
Processes Affected by Predictor=Sediment Only
Hydraulics Update Threshold= 0.02
Energy Slope Method= 1
Volume Change Method= 1
Sediment Retention Method= 0
Sediment TS Multiplier= 1
Warm Up Method= 0
XS Weighting Method= 0
Number of US Weighted Cross Sections= 1
Number of DS Weighted Cross Sections= 1
Upstream XS Weight=0
Main XS Weight=1
Downstream XS Weight=0
Number of DS XS's Weighted with US Boundary= 1
Upstream Boundary Weight= 1
Weight of XSs Associated with US Boundary= 0
Number of US XS's Weighted with DS Boundary= 1
Downstream Boundary Weight= 0.5
Weight of XSs Associated with DS Boundary= 0.5
Percentile Method= 0
Sediment Output Level= 3
Mass or Volume Output= 0
Output Increment Type= 1
Profile and TS Output Increment= 1
Transport Output Increment 1
XS Output Flag= 0
XS Output Increment= 10
Read HDF5 Sediment Hotstart= 0
Sediment Hotstart Type= 0
Write Gradation File= 0
Read Gradation Hotstart= 0
Write HDF5 File= 1
Write Binary Output= 1
Write DSS Sediment File= 0
DSS Sediment Output Type= 1
SV Curve= 0
Specific Gage Flag= 0
Subcell Erosion Methods= 0
Subcell Deposition Methods= 0
Advection Scheme= 1
Matrix Solver= 0
Implicit Weighting Factor= 1
Maximum Outer Loop Convergence Iterations= 5
Convergence Maximum Absolute= 0.001
Convergence RMSE= 0.0001
Grain Fractions Max Abs Error= 0.001
Max Subgrid Regions= 1
Max Subgrid Length Scale= 3.402823E+38
Initial Layer Thickness= 3
Min Layer Thickness= 0.1
Max Layer Thickness= 6
Number of Layers= 5

--- CedrRn.f01 (steady flow) ---

Flow Title=Flow
Program Version=6.60
Number of Profiles= 1
Profile Names=P100yr
River Rch & RM=CedrRn,Main,8100
     793
River Rch & RM=CedrRn,Main,6301
     898
River Rch & RM=CedrRn,Main,2400
     999
Boundary for River Rch & Prof#=CedrRn,Main            , 1
Up Type= 0
Dn Type= 3
Dn Slope=0.021369
DSS Import GetInterval= 0
DSS Import GetPeak= 0
DSS Import FillOption= 0

--- CedrRn.g01 (geometry) ---

Geom Title=Geometry
Program Version=6.60

River Reach=CedrRn          ,Main
Reach XY= 30
     1661075.456      464106.291     1660995.387      463954.447
     1660857.142       463839.02     1660830.635      463491.396
     1660749.097      463320.604     1660744.064      463128.001
     1660651.454      462947.814     1660644.743       462713.94
     1660716.843      462417.822     1660377.314      462105.262
     1660024.617      461504.759       1659254.1      461247.275
     1658885.007      461284.848     1658805.625      461356.663
     1658586.514      461387.533     1658447.599      461475.445
     1658106.686      461438.871     1657727.521      461285.528
     1657623.502      461085.879     1657630.884      460976.155
     1657734.169      460815.073     1657919.242      460731.187
     1658089.112      460524.093     1658158.842      460498.928
     1658277.855      460194.841     1658203.931      460049.088
     1657952.273      459860.345     1657553.813      459810.537
     1657615.104       459694.08     1657558.982      459620.781

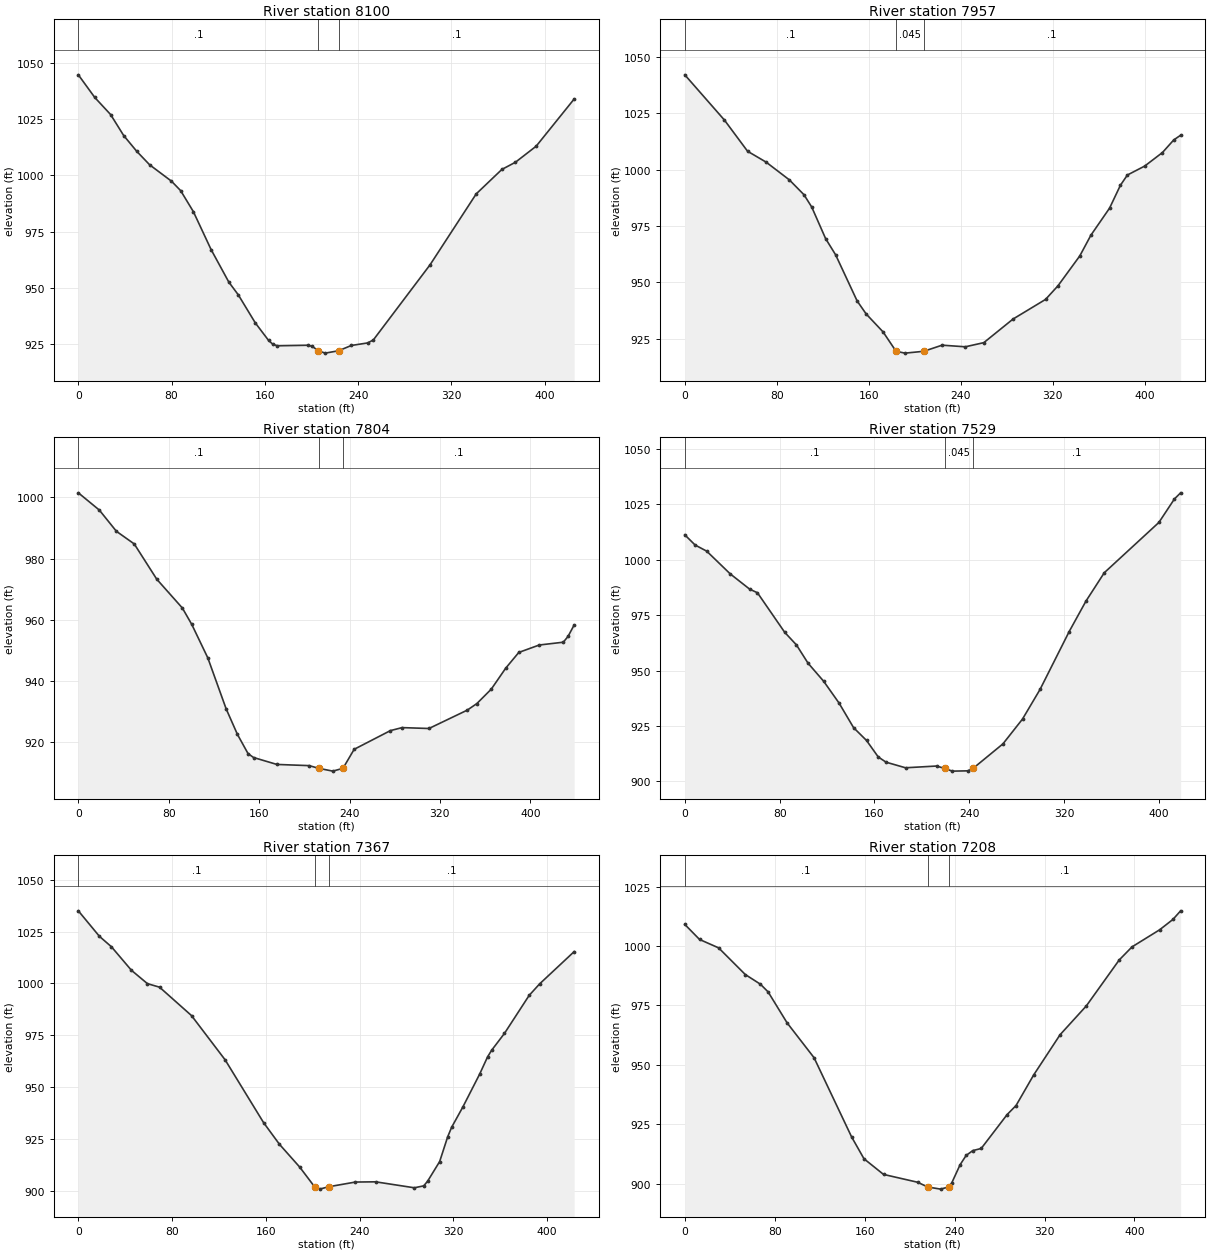
Type RM Length L Ch R = 1 ,8100    ,146.5,143,142.9
XS GIS Cut Line= 6
1661253.79875134 463988.951585011661176.55448325464030.597499087
1661111.66288076464068.254247919 1661023.8730301464116.138994679
1660957.08018467464150.309858084 1660878.7135435464189.366210416
#Sta/Elev= 30
       0 1044.92    14.1 1034.82    27.7 1027.19    38.9 1017.84    50.1  1010.8
    61.2 1004.76    79.9  997.47    87.8  993.23    98.7  983.86   113.9  966.95
   129.1  952.44   137.2  946.77   151.8  934.25   163.2  926.42   166.9  924.68
   170.7     924   196.8  924.24   200.6  923.76  205.97921.7838   211.8  920.73
  223.27921.7825   234.2  924.14   248.2  925.28   253.1  926.61   301.8  960.17
   341.4  991.81   363.4 1002.71     375  1005.9   392.8 1013.07   425.4 1034.13
#Mann= 3 ,-1,0
       0      .1       0  205.97    .045       0  223.27      .1       0
Bank Sta=205.97,223.27
XS Rating Curve= 0 ,0
Exp/Cntr(USF)=0,0
Exp/Cntr=0.3,0.1

Type RM Length L Ch R = 1 ,7957    ,156.8,152.7,152.4
XS GIS Cut Line= 2
1661168.88537964463847.4463460181660817.71652943  464097.8758493
#Sta/Elev= 30
       0 1042.09    34.5 1021.99    54.6 1008.17    70.7 1003.35    90.9  995.48
   103.7  988.85   110.4  983.41   122.5  969.38   131.2  962.19   149.9  941.72
   157.8  935.91   172.5  927.95   183.8  919.34   191.6  918.55  207.87919.3608
   223.8  922.08     244  921.36   260.1   923.2   285.5  933.67   313.8  942.39
   324.6  948.43   343.6  961.71   353.3  970.94   369.5  982.92   378.9  993.05
     385  997.62   400.1  1001.6   415.5  1007.6   425.3 1013.18   431.3 1015.28
#Mann= 3 ,-1,0
       0      .1       0   183.8    .045       0  207.87      .1       0
Bank Sta=183.8,207.87
XS Rating Curve= 0 ,0
Exp/Cntr(USF)=0,0
Exp/Cntr=0.3,0.1

Type RM Length L Ch R = 1 ,7804    ,264.7,275.3,280.7
XS GIS Cut Line= 6
1661067.97825684 463743.000305251660986.67526984463793.892920002
1660919.16162534463836.3387012481660848.80677918463908.231274009
1660801.17334425463966.1625885961660745.60094884 464033.74906759
#Sta/Elev= 30
       0 1001.52    18.6  995.87    33.7  988.93    49.5  984.79    69.4  973.26
    92.1  963.81   100.4  958.45   114.6   947.5   130.8  930.84   140.8  922.47
   150.2  916.18   155.1   914.9   175.7  912.64   204.3  912.25  212.82911.3631
   225.2  910.45  234.21911.3635   244.1  917.59   276.2  923.71   286.5  924.69
   310.3   924.4   344.2  930.41   352.7  932.56   365.5   937.3   378.2  944.13
   389.8  949.29   407.9  951.72   429.2  952.64   433.4  954.54   438.8  958.28
#Mann= 3 ,-1,0
       0      .1       0  212.82    .045       0  234.21      .1       0
Bank Sta=212.82,234.21
XS Rating Curve= 0 ,0
Exp/Cntr(USF)=0,0
Exp/Cntr=0.3,0.1

Type RM Length L Ch R = 1 ,7529    ,161.3,161.9,159.7
XS GIS Cut Line= 2
1661041.22174868463601.3234232521660623.83255506463629.063468087
#Sta/Elev= 30
       0 1011.19     8.7 1006.59    18.5 1003.82    38.3  993.59    54.7  986.71
    61.3  985.06    84.3  967.23    94.2  961.55     104   953.3   117.2  945.14
   130.1  935.38   142.4  924.25   153.3  918.49   163.2  911.05   169.8  908.69
   186.2  906.17   212.5  906.96   219.1  905.88   225.7  904.66   238.8  904.79
  243.15  905.88   268.4  916.95   284.9  928.13   299.7  941.49   324.3   967.6
   338.4  981.27   353.9   994.1     400 1016.79   413.1 1027.38   418.3 1030.12
#Mann= 3 ,-1,0
       0      .1       0   219.1    .045       0  243.15      .1       0
Bank Sta=219.1,243.15
XS Rating Curve= 0 ,0
Exp/Cntr(USF)=0,0
Exp/Cntr=0.3,0.1

Type RM Length L Ch R = 1 ,7367    ,160.4,159.6,156.7
XS GIS Cut Line= 2
1661017.06692723463406.179629187 1660610.5623794463523.945344612
#Sta/Elev= 30
       0 1035.09      18 1022.77    28.3  1017.7    45.3 1006.38      59  999.91
    69.3  998.22    96.6  984.49   125.3  963.11   158.1   932.8   171.7   922.3
   188.9  911.35  201.62901.8238   205.9  900.67  213.83901.8315   236.5  904.09
   253.7   904.2   286.8  901.32   294.8  902.25   298.1  904.49   308.4  913.99
   315.2  925.86   318.6  930.52   328.2  940.35   342.5  956.18   349.3  964.55
   352.8  967.77   363.7  975.88   384.8  994.25   393.7  999.79   423.2 1015.39
#Mann= 3 ,-1,0
       0      .1       0  201.62    .045       0  213.83      .1       0
Bank Sta=201.62,213.83
XS Rating Curve= 0 ,0
Exp/Cntr(USF)=0,0
Exp/Cntr=0.3,0.1

Type RM Length L Ch R = 1 ,7208    ,304.9,306.7,306
XS GIS Cut Line= 6
1660969.84721951463256.742091417   1660880.66039463279.552741334
 1660802.6703885463302.4053859261660712.03703959463354.339993343
1660649.24976359463395.5820368381660570.46120726463435.119687423
#Sta/Elev= 30
       0 1009.08    13.1 1002.76    30.1  999.21    53.8     988    67.3  983.91
    74.1  980.69      91  967.66     115  952.98   148.4  919.65   159.4  910.46
   176.8  903.87   207.1  900.58  216.01898.5892   227.6  897.68   234.6  898.59
   237.3   900.1   244.9  907.93   250.3  911.87   256.2  913.89   263.7  914.79
   286.8  929.08   294.7  932.87   310.4  945.75   333.9  962.68   357.2  974.78
   386.5  994.14   397.9  999.64   422.4 1006.81   434.3  1011.2   441.1  1014.8
#Mann= 3 ,-1,0
       0      .1       0  216.01    .045       0   234.6      .1       0
Bank Sta=216.01,234.6
XS Rating Curve= 0 ,0
Exp/Cntr(USF)=0,0
Exp/Cntr=0.3,0.1

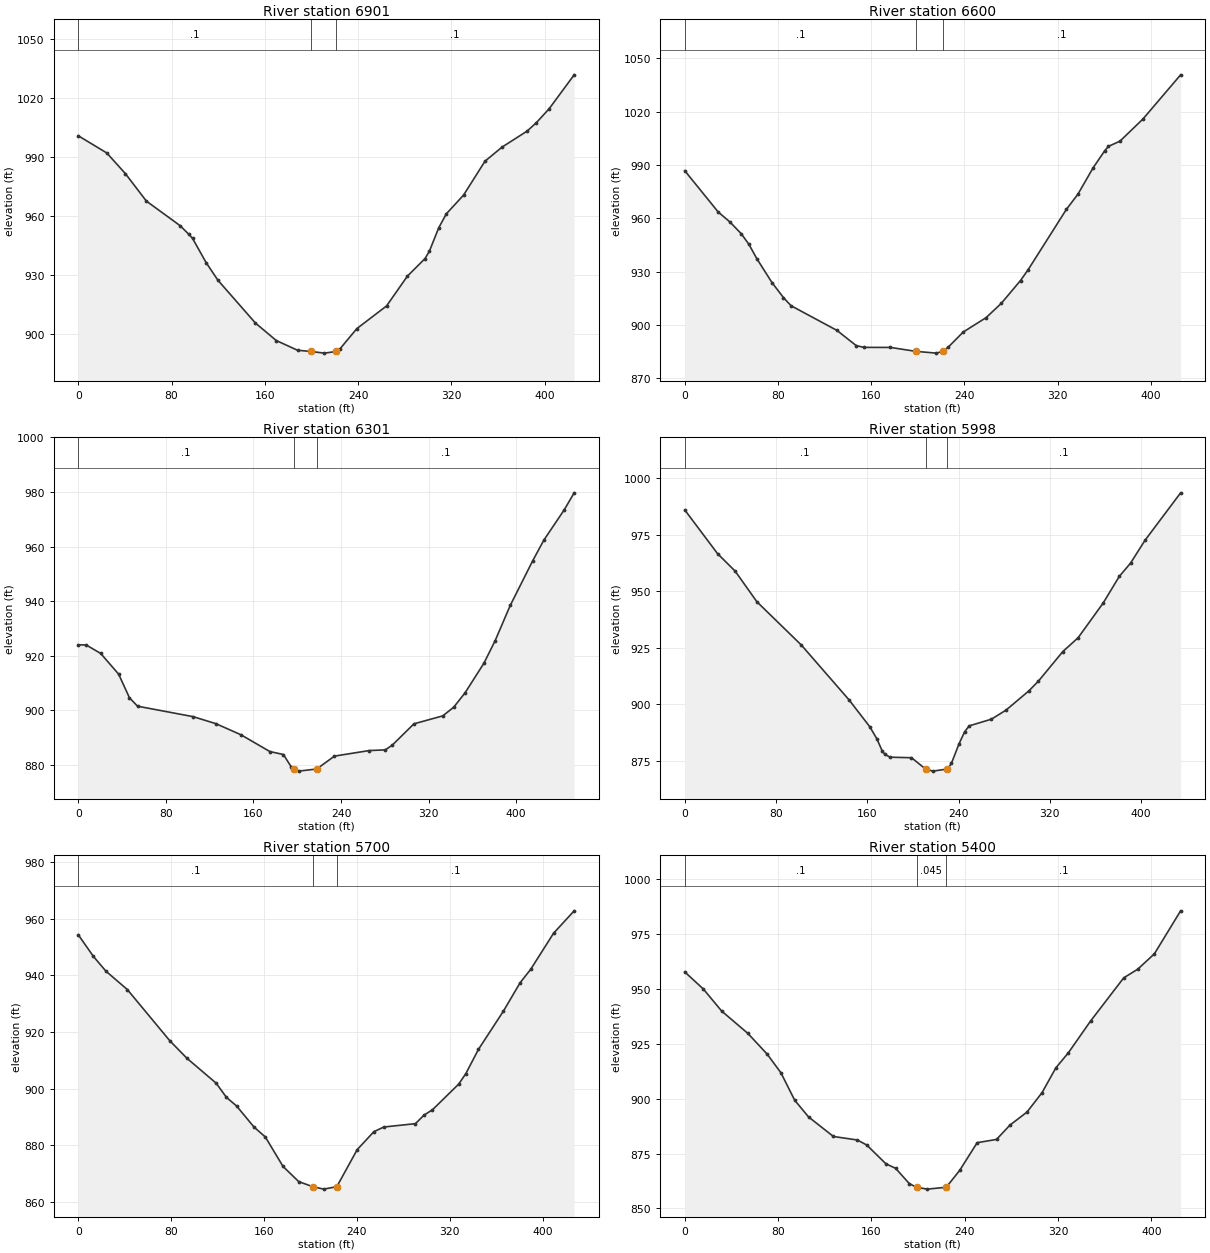
Type RM Length L Ch R = 1 ,6901    ,294.1,300.9,304.2
XS GIS Cut Line= 6
1660888.73189618462953.1708481761660809.06998201 462989.91322875
  1660740.302403 463020.083115921660650.09851517 463063.28217651
1660583.01695642463096.8241041751660504.75497384463135.955915675
#Sta/Elev= 30
       0 1000.64    24.4  991.91    40.3  981.45    58.4  967.42    87.2  954.99
    94.5  950.72      98  948.45   109.6  936.18   119.7  927.22   151.9  905.43
   169.8  896.53     188   891.6  199.57890.9665   211.1  890.13  221.18890.9665
   224.4  892.29   238.9   902.6   264.4  914.13   282.3  929.31   297.4  938.23
   301.1  941.94   309.2  953.93   315.7  960.99   330.4  970.45   348.8  987.71
   363.4  994.87     385 1003.05   392.8 1007.26   403.8 1014.35   425.3 1031.64
#Mann= 3 ,-1,0
       0      .1       0  199.57    .045       0  221.18      .1       0
Bank Sta=199.57,221.18
XS Rating Curve= 0 ,0
Exp/Cntr(USF)=0,0
Exp/Cntr=0.3,0.1

Type RM Length L Ch R = 1 ,6600    ,298.1,298.9,299.9
XS GIS Cut Line= 6
1660857.80052759 462758.307720841660770.07859017462751.524269834
1660695.07874018462751.5242698341660595.07861209462751.524269834
1660520.07843401462751.524269834  1660432.578609462751.524269834
#Sta/Elev= 30
       0  986.75    28.7  963.51    38.6  958.01    48.5  951.28    55.1  945.26
    61.8  937.28    74.8  923.83    84.7  915.33    91.2  910.78   130.6  896.89
     147   888.4   153.6  887.34   176.5  887.32  198.33885.0951   215.9  884.11
  221.22885.0944   225.8  887.29   238.9  895.97   258.6   904.1   271.7  912.19
   288.1  924.98   294.7  931.11   327.5  965.05   337.3  973.49   350.4  988.42
   360.3  997.93   363.5 1000.46   373.4 1003.39   393.1 1015.82   425.5 1040.74
#Mann= 3 ,-1,0
       0      .1       0  198.33    .045       0  221.22      .1       0
Bank Sta=198.33,221.22
XS Rating Curve= 0 ,0
Exp/Cntr(USF)=0,0
Exp/Cntr=0.3,0.1

Type RM Length L Ch R = 1 ,6301    ,315.7,303.2,297.1
XS GIS Cut Line= 6
1660938.07661375462480.5415440951660850.77035792462474.721345752
1660775.93651809462469.7325105821660676.00889643462465.315524668
1660596.59829409462475.9532986731660490.96497518462508.055596679
#Sta/Elev= 30
       0  924.02     7.2  923.97    20.4  920.88    36.8   913.3    46.7  904.64
    54.1  901.54   104.9  897.71   125.6  895.15   148.6  891.07   174.9  884.94
   187.4  883.83   194.6  879.24  196.68878.5214   201.2  877.75  217.79878.5234
     234  883.25   265.8  885.29   280.4  885.53   286.8  887.26   306.6  895.08
     333     898     343  901.19   353.3  906.43   370.5  917.25   380.8  925.54
   394.6  938.46     415  954.73   425.3  962.39   443.9  973.47     453  979.72
#Mann= 3 ,-1,0
       0      .1       0  196.68    .045       0  217.79      .1       0
Bank Sta=196.68,217.79
XS Rating Curve= 0 ,0
Exp/Cntr(USF)=0,0
Exp/Cntr=0.3,0.1

Type RM Length L Ch R = 1 ,5998    ,291.4,297.7,301
XS GIS Cut Line= 6
1660662.86226918462098.2375186681660606.81087209462171.610731512
1660557.96287267462233.1653984191660494.23301326462311.799427509
1660444.61139335462368.0371759241660386.71944876462433.648265168
#Sta/Elev= 30
       0  986.02    28.7  966.71    44.2  958.93    63.2  945.41   102.1  926.29
     144  901.98   162.1  890.14   168.4  884.72     173  879.44   175.4  877.88
     180  876.63   198.7   876.4  211.07 871.402   217.4  870.47   230.2871.3986
   233.7  873.91   240.4  882.59   245.3   887.9   249.3   890.5   268.7  893.44
   281.6  897.48   301.5  905.94   309.8   910.2   331.4   923.4   344.8  929.52
   366.7  944.84   380.8   956.6   390.7   962.5   403.5  972.69   434.6  993.61
#Mann= 3 ,-1,0
       0      .1       0  211.07    .045       0   230.2      .1       0
Bank Sta=211.07,230.2
XS Rating Curve= 0 ,0
Exp/Cntr(USF)=0,0
Exp/Cntr=0.3,0.1

Type RM Length L Ch R = 1 ,5700    ,301.8,300.2,298.9
XS GIS Cut Line= 6
1660538.61481425461953.229278505  1660459.157296461993.996913508
1660389.58361626462022.8318295931660298.28360201462063.795330346
1660229.99732126462094.7342448381660150.33540709462130.828004673
#Sta/Elev= 30
       0  954.33      13  946.71    23.8   941.5    42.2  935.02    78.8  916.94
    93.6  910.73   118.7  901.97   127.6  896.94   136.3  893.91   151.3  886.48
   161.1  882.95   176.3  872.57   189.8  867.21  201.92865.4037   211.4  864.54
  222.64 865.404   240.2  878.48   254.6  884.84   263.2  886.48   290.4  887.66
   297.8  890.69     305  892.54   327.6  901.61   333.8  905.34   344.6  913.85
   366.2  927.43   380.6  937.46   389.6  942.13   409.4  954.92   427.1  962.82
#Mann= 3 ,-1,0
       0      .1       0  201.92    .045       0  222.64      .1       0
Bank Sta=201.92,222.64
XS Rating Curve= 0 ,0
Exp/Cntr(USF)=0,0
Exp/Cntr=0.3,0.1

Type RM Length L Ch R = 1 ,5400    ,301.2,300.2,296.9
XS GIS Cut Line= 6
1660360.17028926461678.2127681671660286.99491067461726.188065916
1660224.27357942461767.3100309221660140.64513776 461822.13997376
1660077.92347842461863.2616106721660004.74842793  461911.2372365
#Sta/Elev= 30
       0   957.7    15.9  949.94    31.6   939.9      54  929.76    70.6   920.3
    82.4  911.79    94.2   899.3   106.1  891.68   127.4  882.79   147.9  881.19
   155.9  878.93   172.4  870.35   180.7  868.31   192.4  861.35  198.63859.6683
   207.8  858.82  224.08859.6685   235.6  867.33   250.6  879.97   267.2  881.45
   278.7  887.97   293.3   893.9   306.2  902.74     318     914   328.8  920.92
   347.8  935.35   376.2  955.01   388.1  958.91   402.5  965.95     425  985.54
#Mann= 3 ,-1,0
       0      .1       0  198.63    .045       0  224.08      .1       0
Bank Sta=198.63,224.08
XS Rating Curve= 0 ,0
Exp/Cntr(USF)=0,0
Exp/Cntr=0.3,0.1

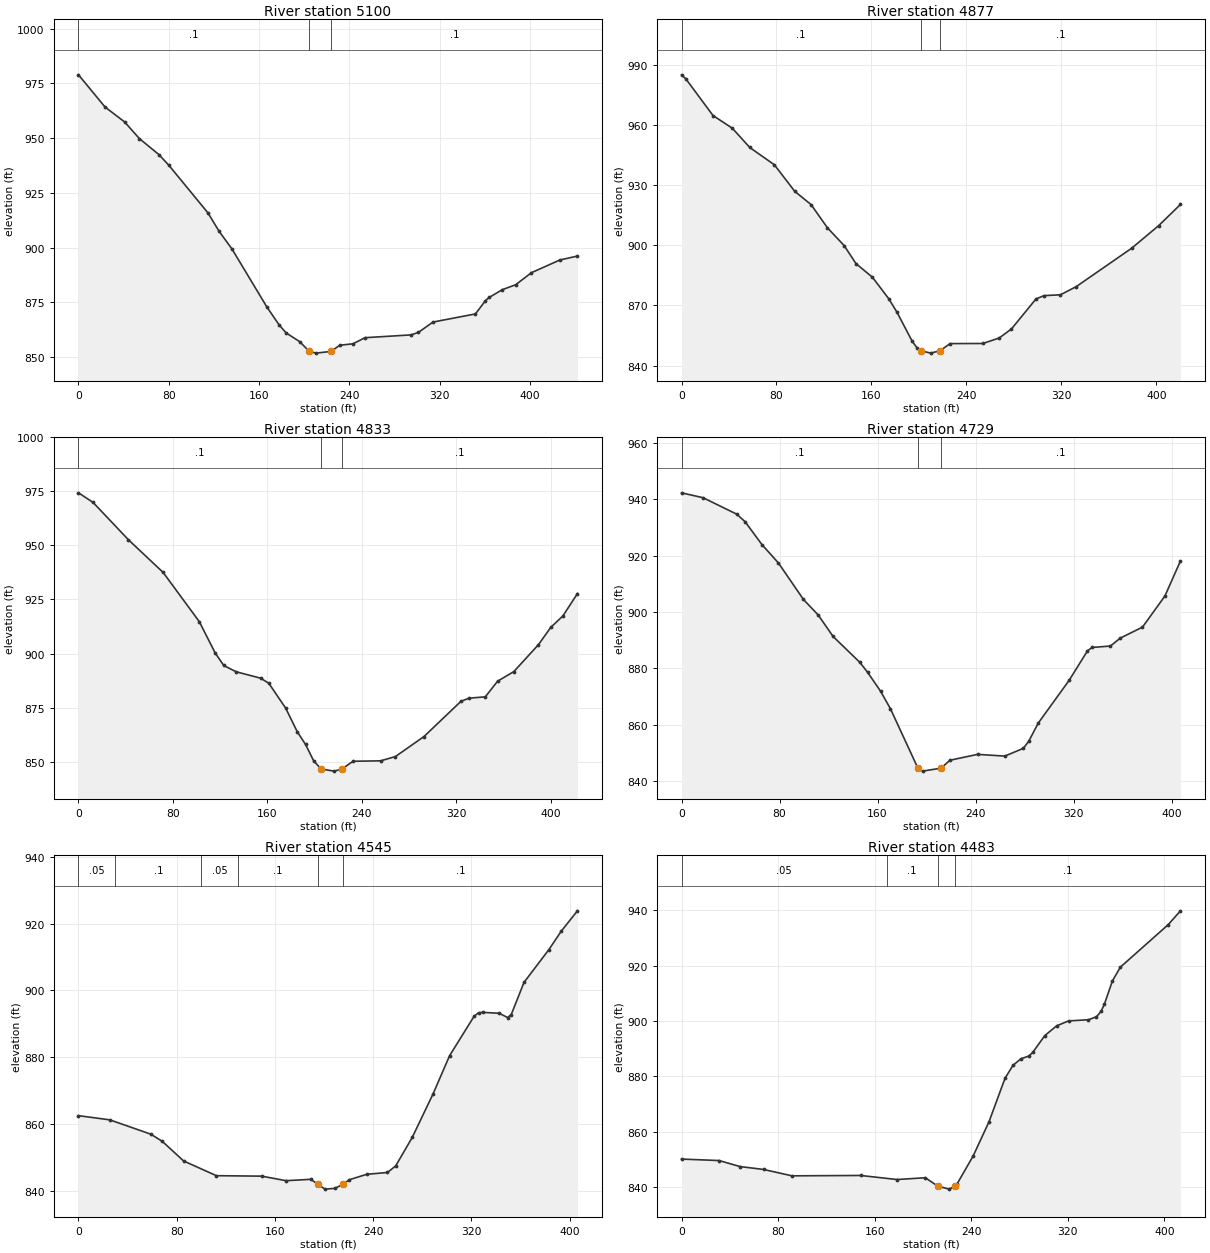
Type RM Length L Ch R = 1 ,5100    ,225.8,223,217.8
XS GIS Cut Line= 6
1660189.93834625461367.5388488321660132.63203043461433.661748096
1660083.51270609461490.3388000881660017.65785092461565.593898922
1659962.28033701461625.8841326681659896.08361901  461697.8990805
#Sta/Elev= 30
       0  978.96    23.5  964.28    40.9  957.44    53.9  949.88    71.3  942.52
      80  937.72   114.7  915.94   124.6  907.53   136.1  899.38   166.8  873.08
   178.1  864.57   184.2  861.03     196  857.15  204.51852.6776   210.7  851.88
  223.86 852.678   231.6  855.49   243.2  856.13     254  858.93   294.8  860.21
   301.3  861.37   314.2  866.07   351.8  869.78   360.7  875.85     364  877.32
   375.6  880.85   387.5  883.12   401.4   888.6   426.7  894.43   442.2   896.2
#Mann= 3 ,-1,0
       0      .1       0  204.51    .045       0  223.86      .1       0
Bank Sta=204.51,223.86
XS Rating Curve= 0 ,0
Exp/Cntr(USF)=0,0
Exp/Cntr=0.3,0.1

Type RM Length L Ch R = 1 ,4877    ,44,44.1,44.2
XS GIS Cut Line= 2
1659909.50243309461255.0619196431659781.80466937461655.496882396
#Sta/Elev= 30
       0  985.12     3.6  983.15    26.5  964.81    42.8  958.46    57.5  948.84
    78.2  940.22    95.4  926.95   109.2   920.3   122.9  908.75     137  899.87
     147  890.85   160.8  884.08   174.6  873.31   181.5   866.6   194.2  852.23
   198.7  848.54  201.42847.4204   209.9  846.18  217.96847.4179   226.2  850.94
   253.8  850.99   267.6  853.73   277.9  858.23   298.6  873.25   305.4  874.89
   319.2   875.3   332.6  879.42   379.3   898.6   401.9  909.82   420.3  920.41
#Mann= 3 ,-1,0
       0      .1       0  201.42    .045       0  217.96      .1       0
Bank Sta=201.42,217.96
XS Rating Curve= 0 ,0
Exp/Cntr(USF)=0,0
Exp/Cntr=0.3,0.1

Type RM Length L Ch R = 1 ,4833    ,102.2,103.7,105.4
XS GIS Cut Line= 2
1659871.45972426461239.1138063111659737.52478869461639.678693733
#Sta/Elev= 30
       0  974.29    12.3  969.88    42.3  952.59    71.7  937.49   102.3  914.74
   115.8  900.21     123  894.51   133.4  891.61   154.2  888.64   161.1   886.3
   175.4   874.8   185.3  863.79   192.2  858.05   199.1  850.43  205.48846.6548
   216.4  845.69  223.02 846.653   232.4  850.25   255.8  850.45   268.3  852.42
   292.5  861.68   323.7   877.9   330.6   879.4   344.4  880.02   354.8  887.24
   368.6  891.71   389.4  904.13   399.8   912.1   410.1  917.41   422.4  927.75
#Mann= 3 ,-1,0
       0      .1       0  205.48    .045       0  223.02      .1       0
Bank Sta=205.48,223.02
XS Rating Curve= 0 ,0
Exp/Cntr(USF)=0,0
Exp/Cntr=0.3,0.1

Type RM Length L Ch R = 1 ,4729    ,197.9,183.6,177.7
XS GIS Cut Line= 2
1659807.41022597461219.283620396 1659612.0974598461576.627156711
#Sta/Elev= 30
       0  942.36    17.6  940.62    44.9  934.82    51.8  932.15    65.8  923.89
    79.1  917.45    99.5   904.5   111.6  898.95   123.7  891.35   145.5  882.17
   151.8  878.68   162.4  871.94   170.5  865.69  192.92844.5818   196.7  843.53
  211.78844.5842   219.1   847.4   241.6  849.48   263.9  848.87   278.9  851.61
   283.3  854.08   291.2  860.63   316.3  875.75   331.3  886.24     335  887.45
     350  887.95   358.2   890.8   376.2  894.67   394.5  905.71   407.2  918.17
#Mann= 3 ,-1,0
       0      .1       0  192.92    .045       0  211.78      .1       0
Bank Sta=192.92,211.78
XS Rating Curve= 0 ,0
Exp/Cntr(USF)=0,0
Exp/Cntr=0.3,0.1

Type RM Length L Ch R = 1 ,4545    ,54.1,62.6,66.4
XS GIS Cut Line= 4
1659568.43278817461133.9247017711659532.40631198461320.759682952
1659552.09520013461350.5024714361659510.62286126461526.026814743
#Sta/Elev= 30
       0  862.46    25.5   861.2    58.9  856.91    68.2  854.77    85.6  848.88
   112.3  844.47   149.1  844.33   169.1  842.97   189.2  843.38  194.82841.9132
   200.8  840.44   208.7  840.67  215.58841.9149   220.5  843.25   234.7  844.88
   251.6  845.43   258.3   847.4   271.8  855.96   288.7  868.95   302.2  880.44
   322.2  892.28   325.8   893.3   329.1  893.42   342.6  893.14   349.4  891.87
   352.4  892.76   362.8  902.41   383.1  912.25   393.2  917.79   406.3  923.85
#Mann= 6 ,-1,0
       0     .05       0      30      .1       0     100     .05       0
     130      .1       0  194.82    .045       0  215.58      .1       0
Bank Sta=194.82,215.58
XS Rating Curve= 0 ,0
Exp/Cntr(USF)=0,0
Exp/Cntr=0.3,0.1

Type RM Length L Ch R = 1 ,4483    ,288.9,282.6,281
XS GIS Cut Line= 3
1659523.66015126461125.1010135111659482.28173176461327.940072768
1659461.55382591461533.329464442
#Sta/Elev= 30
       0  850.11    31.2  849.58    48.4  847.41      68  846.36    91.5  844.06
   148.4  844.19   178.5  842.73     202  843.37  212.33840.3414   221.9  839.26
  226.32840.3395   228.4  841.21   241.6   851.2   254.8  863.62     268  879.25
   274.6  883.94   281.2  886.33   287.8  887.31   291.1  888.68     301   894.7
   310.8  898.22   320.7     900   337.2  900.42   343.8   901.5   347.7  903.48
   350.4  906.09     357  914.43   363.6  919.41   403.2  934.74   413.4  939.75
#Mann= 4 ,-1,0
       0     .05       0     170      .1       0  212.33    .045       0
  226.32      .1       0
Bank Sta=212.33,226.32
XS Rating Curve= 0 ,0
Exp/Cntr(USF)=0,0
Exp/Cntr=0.3,0.1

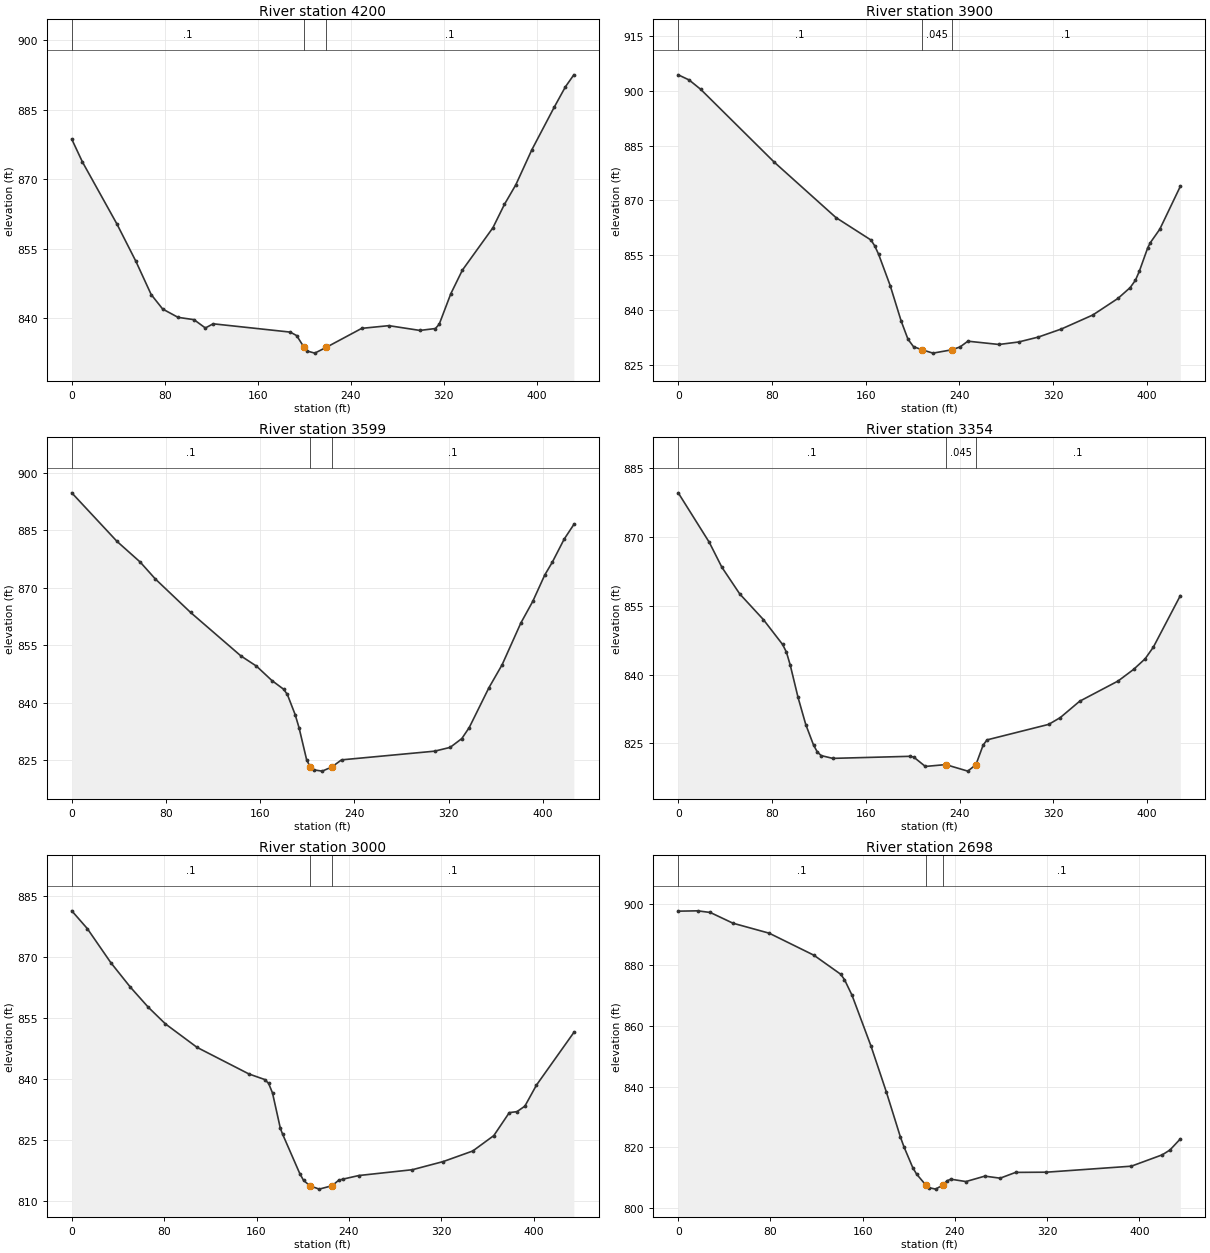
Type RM Length L Ch R = 1 ,4200    ,296.3,300,296.9
XS GIS Cut Line= 6
1659189.19264434461041.5283460021659194.92229168461129.480926007
1659210.10959725461202.9581412521659233.12956434461300.272579178
 1659244.6144495461375.5811555831659240.15678126461467.961548254
#Sta/Elev= 30
       0  878.61     9.2  873.69    38.8  860.35    55.2  852.27    68.3  845.13
    78.2  842.01    91.4  840.22   105.1  839.72   114.9  837.93   121.6  838.83
   187.9  837.04   193.4  836.29  199.78833.7634   202.2  832.98     209  832.51
  218.94833.7646   249.4  837.85   272.7  838.43   299.4   837.4   312.7  837.81
     316  838.73     326  845.32   335.9  850.38   362.2  859.53   372.1  864.56
   381.9  868.79   395.7  876.34   414.8  885.45   424.6  889.92   431.8  892.48
#Mann= 3 ,-1,0
       0      .1       0  199.78    .045       0  218.94      .1       0
Bank Sta=199.78,218.94
XS Rating Curve= 0 ,0
Exp/Cntr(USF)=0,0
Exp/Cntr=0.3,0.1

Type RM Length L Ch R = 1 ,3900    ,297.5,301.2,297.3
XS GIS Cut Line= 6
1658915.89561875461064.3859118371658924.07965751461151.587509096
1658932.72596568461226.1136067511658946.86766967461325.108815596
1658961.59959559461399.2484310871658989.68221658461485.067485169
#Sta/Elev= 30
       0  904.42     9.3  903.01    19.2  900.44    81.8  880.54   134.6  865.32
   164.5  859.17   167.7  857.57     171  855.27   180.9  846.69   190.3  836.94
   196.1  831.98   200.8  829.96  208.09829.1057   217.4  828.19  233.61829.1064
   240.6   829.9   247.2  831.46   273.8  830.56   290.5  831.24   307.3  832.59
     327   834.8   353.8  838.63   375.3  843.18   385.7  846.14   390.2  848.15
   393.5   850.6   400.6  856.96   402.9  858.44     411  862.14   428.5  873.87
#Mann= 3 ,-1,0
       0      .1       0  208.09    .045       0  233.61      .1       0
Bank Sta=208.09,233.61
XS Rating Curve= 0 ,0
Exp/Cntr(USF)=0,0
Exp/Cntr=0.3,0.1

Type RM Length L Ch R = 1 ,3599    ,239.5,244.6,242.5
XS GIS Cut Line= 6
1658658.91516159461156.7476037591658665.44762884461244.217573166
1658670.31638551461319.2659794991658672.03291751461419.362236008
1658680.72089225461494.0799343441658697.94887617461580.349446833
#Sta/Elev= 30
       0  894.83    38.4  882.15    58.1  876.75    70.9  872.35   100.9  863.59
   143.6  852.24   156.8  849.58   169.9  845.82   179.8  843.56     183  842.19
   189.6  836.95   192.9  833.54   199.4   825.1  202.45823.2583     206  822.47
   212.6  822.17  220.76823.2576     229  825.11     308  827.38   321.2  828.37
   331.1  830.67   337.4  833.55   354.1  843.94   365.3  849.94   381.2  860.84
   391.3  866.48   401.5  873.37     408  876.77     418  882.75   426.2  886.57
#Mann= 3 ,-1,0
       0      .1       0  202.45    .045       0  220.76      .1       0
Bank Sta=202.45,220.76
XS Rating Curve= 0 ,0
Exp/Cntr(USF)=0,0
Exp/Cntr=0.3,0.1

Type RM Length L Ch R = 1 ,3354    ,345.2,353.9,354.5
XS GIS Cut Line= 2
1658440.41053835461227.6316946661658472.38011896461654.694302004
#Sta/Elev= 30
       0  879.61    26.5  868.81    37.2   863.4    52.5  857.56    72.6  851.99
      89  846.56    92.3  844.88    95.6     842   102.2  835.01   108.8  829.09
   115.4  824.64   118.6  823.14   121.9  822.33   131.8  821.72   197.6  822.17
   200.9     822   210.8  819.96  228.18820.3644     247  818.94  253.93 820.338
   260.1  824.61   263.4  825.75     316  829.13   325.9  830.61   342.4  834.17
   375.3   838.6   388.4  841.11   398.3  843.43   405.3  845.97   428.3  857.19
#Mann= 3 ,-1,0
       0      .1       0  228.18    .045       0  253.93      .1       0
Bank Sta=228.18,253.93
XS Rating Curve= 0 ,0
Exp/Cntr(USF)=0,0
Exp/Cntr=0.3,0.1

Type RM Length L Ch R = 1 ,3000    ,299.5,302.7,298.7
XS GIS Cut Line= 6
1658179.76552933461227.8334195911658157.12318617461318.758762673
1658133.34633084461393.5207522511658111.37196533461491.078628004
1658095.34443834461564.3458699291658076.64532876461649.824701592
#Sta/Elev= 30
       0  881.32    13.5  876.94    33.8  868.59    50.7  862.58    66.2  857.65
    81.1  853.54   108.5  847.77   153.4  841.24     167  839.88   170.4  838.94
   173.8  836.57   180.6  827.88   182.6  826.41   197.4  816.78   200.7  815.09
  206.17813.7854   214.2  812.95  225.37813.7845     231  815.11   234.4  815.38
   248.5  816.29   294.9  817.72   321.7  819.73   347.2  822.32   365.4   826.1
   378.8  831.74   385.5  831.99   392.3  833.34   402.3  838.49   434.7  851.44
#Mann= 3 ,-1,0
       0      .1       0  206.17    .045       0  225.37      .1       0
Bank Sta=206.17,225.37
XS Rating Curve= 0 ,0
Exp/Cntr(USF)=0,0
Exp/Cntr=0.3,0.1

Type RM Length L Ch R = 1 ,2698    ,291.8,297.6,307
XS GIS Cut Line= 6
1657919.08035517461116.0206510871657867.13262442461194.883354262
1657857.59589809461269.661748007 1657850.3377105 461369.70780775
1657835.59298934461444.8608726711657817.69768393461531.975199759
#Sta/Elev= 30
       0  897.68    16.8  897.79    27.8  897.25    47.5  893.72    78.9  890.44
   117.7   883.2   140.9  876.96   144.2  875.21   150.8  870.02   167.3  853.27
   180.5  838.32   192.8  823.39   195.9  820.16   203.5  813.35   206.8  811.25
  214.74 807.676   217.4  806.81   223.3  806.31  229.67807.6773   233.1  809.01
   236.4  809.58   249.6   808.8     266  810.58   279.3  809.91   292.7  811.81
   319.5  811.88   393.1  813.85   419.9  817.58   426.6  819.17   435.6  822.82
#Mann= 3 ,-1,0
       0      .1       0  214.74    .045       0  229.67      .1       0
Bank Sta=214.74,229.67
XS Rating Curve= 0 ,0
Exp/Cntr(USF)=0,0
Exp/Cntr=0.3,0.1

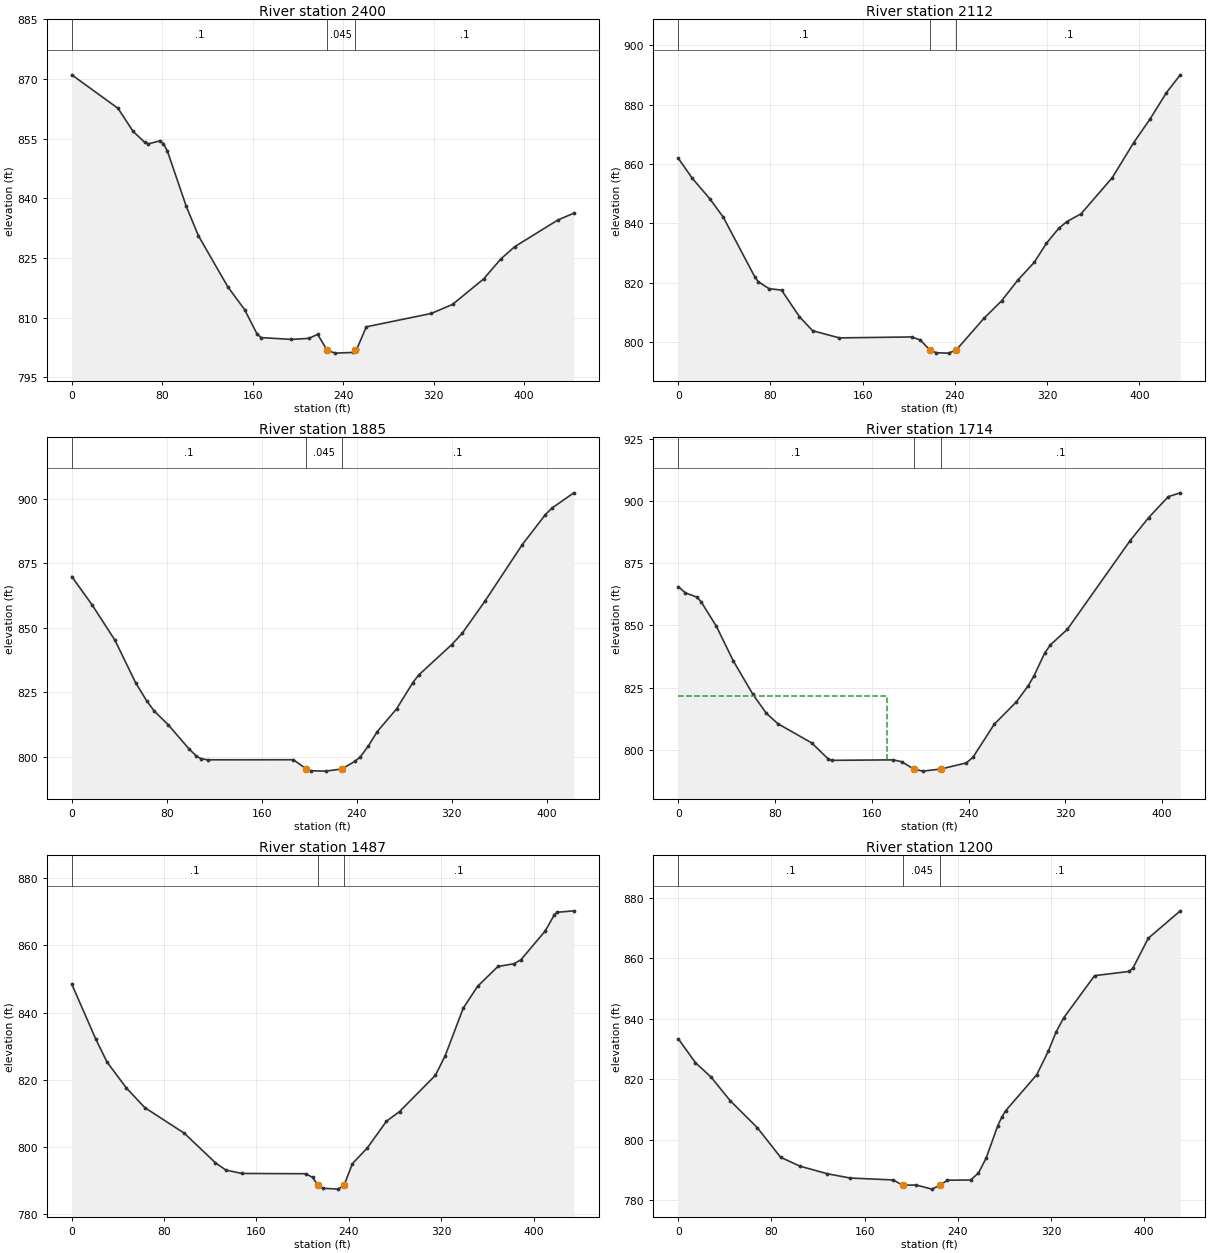
Type RM Length L Ch R = 1 ,2400    ,281.7,288.2,304.3
XS GIS Cut Line= 6
1657867.22612818461059.1838225131657763.42384234461081.209369004
1657697.18972284461116.5760961771657612.32703167461169.533339337
  1657548.395401461208.8912002591657473.78072084461254.768077001
#Sta/Elev= 30
       0  871.03    40.9   862.6    54.3  856.78    64.4  854.07    67.7  853.66
    77.8  854.42    81.1  853.71    84.5  851.89   101.2  837.99   111.9  830.59
   137.9  817.75   152.8  811.99     164  805.75   167.7  804.94   194.2  804.49
   209.7  804.76   217.4  805.76  225.78801.7433   232.9  801.04   248.4  801.21
  250.82801.7421   252.2  802.19   260.4  807.66   317.8  811.01   336.7   813.3
   364.1  819.69   379.5  824.77   391.6  827.81   429.7  834.51   443.9  836.24
#Mann= 3 ,-1,0
       0      .1       0  225.78    .045       0  250.82      .1       0
Bank Sta=225.78,250.82
XS Rating Curve= 0 ,0
Exp/Cntr(USF)=0,0
Exp/Cntr=0.3,0.1

Type RM Length L Ch R = 1 ,2112    ,219.3,227.2,236
XS GIS Cut Line= 6
1657889.86439384460998.5040148461657807.82485976460946.712451767
1657743.17767934460906.7295920961657650.42589634460869.351714101
 1657580.8620591460841.3183056081657501.37960651460804.454862263
#Sta/Elev= 30
       0  861.97    12.3  855.15    27.5  848.24    39.2  842.01    66.3  822.04
    69.4  820.32    78.9  817.95    89.6  817.49   105.2  808.49   116.6  803.78
   139.8  801.36   202.7  801.68   209.8  800.69  218.26797.3135   223.9  796.35
   234.5  796.22  241.28797.3146   265.1  807.91   280.5  813.85   294.6  820.83
   308.8  826.82   319.4  833.23     330  838.27   337.1  840.57   349.5  843.22
   376.6  855.42   395.2  867.26   409.2   875.1   423.6  884.11   435.6   890.1
#Mann= 3 ,-1,0
       0      .1       0  218.26    .045       0  241.28      .1       0
Bank Sta=218.26,241.28
XS Rating Curve= 0 ,0
Exp/Cntr(USF)=0,0
Exp/Cntr=0.3,0.1

Type RM Length L Ch R = 1 ,1885    ,173.3,170.4,165.1
XS GIS Cut Line= 4
1657979.57422242460927.5667326441657912.80030631460848.762224819
 1657844.4586911460719.2997652581657720.73751985 460598.30867188
#Sta/Elev= 30
       0  869.91    17.4  858.73    36.5  845.11    53.7  828.78    63.1   821.7
    69.6  817.67    81.3  812.39    98.6  803.16     105  800.27   108.7  799.32
   114.3  798.86   186.6  798.88  197.51795.3041   201.4  794.62   213.9  794.47
   227.3795.3021   238.2  798.21     243  800.02   249.7  804.22   257.2   809.8
   273.5  818.64   287.2  828.81     292  831.69   319.9  843.52   328.9  848.03
   347.7  860.25   379.3  882.29   398.7  893.88   404.5  896.52   422.7  902.35
#Mann= 3 ,-1,0
       0      .1       0  197.51    .045       0   227.3      .1       0
Bank Sta=197.51,227.3
XS Rating Curve= 0 ,0
Exp/Cntr(USF)=0,0
Exp/Cntr=0.3,0.1

Type RM Length L Ch R = 1 ,1714    ,226.4,227.5,233
XS GIS Cut Line= 2
1658145.77427851460799.7150727761657848.86384025460509.811370521
#Sta/Elev= 30
       0  865.63       6  863.09    15.3  861.43    18.8  859.64    31.6  849.61
    45.5  835.77    61.7  822.32    72.8   814.7    82.2  810.54   110.4  802.75
   124.2   796.2   126.7  795.76   177.7  795.95   184.7   795.2   194.7792.2578
   202.2  791.42  216.99792.2593     238  794.71   243.5  796.92   261.2  810.27
   279.5  819.29   288.9   825.5   293.9  829.58   302.9   838.9   307.6  842.19
   321.6  848.43   373.4  884.05   388.8  893.37   405.1  901.83     415  903.35
#Mann= 3 ,-1,0
       0      .1       0   194.7    .045       0  216.99      .1       0
#XS Ineff= 2 , 0
           172.7  821.57
Permanent Ineff=
       F       F
Bank Sta=194.7,216.99
XS Rating Curve= 0 ,0
Exp/Cntr(USF)=0,0
Exp/Cntr=0.3,0.1

Type RM Length L Ch R = 1 ,1487    ,294,287.2,269.9
XS GIS Cut Line= 5
 1658257.7504706460691.5401066711658172.94641369460549.257582086
 1658130.0086001 460460.63276008 1658087.1012056  460394.8313825
 1658029.8040761460322.512629496
#Sta/Elev= 30
       0  848.46    20.7  832.18    30.5  825.31    47.3  817.58    63.2  811.76
    97.6  804.09   124.3  795.38   133.4  793.18   147.2  792.16   202.7  792.08
   208.7  790.96  213.34788.6108   217.3  787.77   230.8   787.5  235.79788.6156
   243.1  795.07   256.1   799.8   272.6  807.69   283.9  810.56     315  821.35
   323.5  827.21   339.1  841.32   351.5  847.79   369.1   853.7   383.1  854.52
   389.1  855.72   410.1  864.25   418.1  869.13   420.5  869.82   434.9  870.25
#Mann= 3 ,-1,0
       0      .1       0  213.34    .045       0  235.79      .1       0
Bank Sta=213.34,235.79
XS Rating Curve= 0 ,0
Exp/Cntr(USF)=0,0
Exp/Cntr=0.3,0.1

Type RM Length L Ch R = 1 ,1200    ,318,300.6,288.8
XS GIS Cut Line= 6
 1658481.5490465460283.9911471751658395.27067576460269.673590511
  1658321.315115460257.4006491751658222.77823859460240.220565423
1658148.89748085460226.9125211691658055.75002934 460234.91677025
#Sta/Elev= 30
       0  833.39    14.8  825.43    28.1  820.72    44.7  812.84    67.8  803.97
    87.9  794.14   104.6  791.19   128.1  788.69   147.6  787.28   184.4  786.65
  192.72784.9103   204.4  784.97   217.7  783.61  224.83784.9118     231  786.57
     251  786.63   257.7  788.93   264.3  793.88   274.3  804.59   277.7  807.41
     281  809.52   307.7  821.43   317.7  829.27   324.3  835.56     331  840.35
   357.4  854.25   387.1  855.65   390.4   856.8   403.5  866.63     431   875.7
#Mann= 3 ,-1,0
       0      .1       0  192.72    .045       0  224.83      .1       0
Bank Sta=192.72,224.83
XS Rating Curve= 0 ,0
Exp/Cntr(USF)=0,0
Exp/Cntr=0.3,0.1