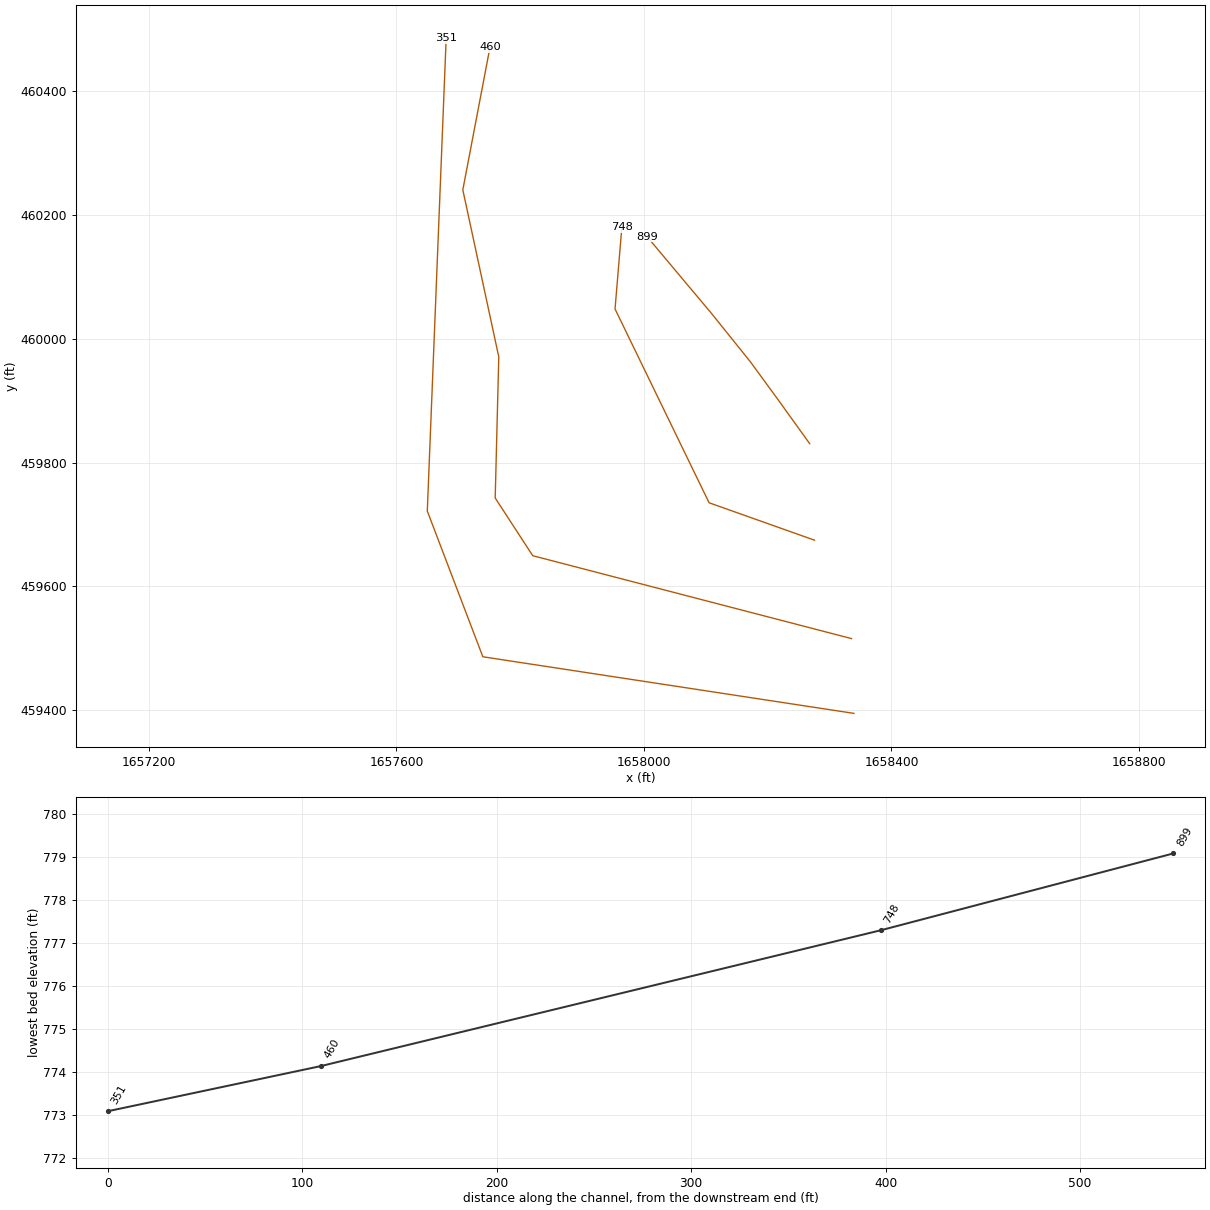
HEC-RAS study CedrRn.prj: CedrRn

--- CedrRn.g01 (geometry) --- (continued)

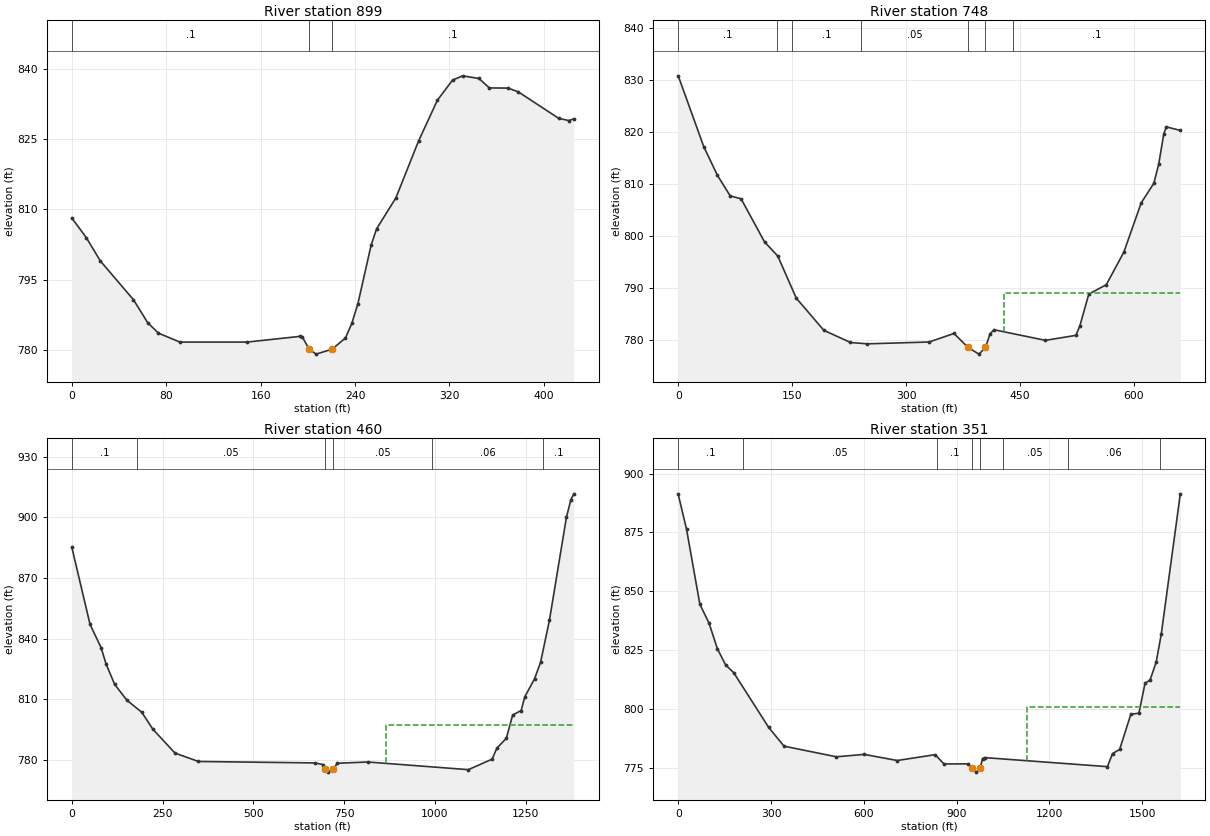
Type RM Length L Ch R = 1 ,899     ,153,150.6,147.9
XS GIS Cut Line= 6
1658267.83195426459830.4621985851658216.60600685459901.699260846
1658172.27735534459962.4074727591658109.61409484460040.366634429
1658061.41766892460097.8304302541658005.18877876460164.872290924
#Sta/Elev= 30
       0  808.12    12.3  803.94    24.2  798.96    52.3  790.68    64.3   785.8
    73.4  783.56    91.6  781.65   148.5  781.65     193  782.86   195.4  782.71
  201.11780.1426     207  779.08  220.64780.1408   231.9  782.52   237.3  785.64
   242.4   789.8   253.6   802.3   258.3  805.83   274.6   812.4   293.9  824.59
   309.8  833.25   322.6  837.53   331.2  838.45     345  837.88   353.8  835.87
   369.7  835.83   378.3  835.03   412.6  829.38   421.1  828.91   425.4  829.27
#Mann= 3 ,-1,0
       0      .1       0  201.11    .045       0  220.64      .1       0
Bank Sta=201.11,220.64
XS Rating Curve= 0 ,0
Exp/Cntr(USF)=0,0
Exp/Cntr=0.3,0.1

Type RM Length L Ch R = 1 ,748     ,293.9,287.9,284.8
XS GIS Cut Line= 4
1658275.53388541 459674.558448321658105.23525694459734.986993907
1657953.24830895460048.1167301271657964.23531724460179.960829588
#Sta/Elev= 30
       0   830.8    33.6  817.18    51.6  811.67    68.4  807.72    82.8  807.15
   113.6  798.87   131.1  796.15   155.4  788.06   191.7  781.87   226.8  779.53
   248.9  779.27   330.3  779.62   363.1  781.26  381.66778.5646     396  777.29
  404.56778.5668   410.5  781.18   415.8  781.98   483.5  779.94   523.6   780.9
   528.8   782.7   540.6  788.84   563.6  790.63   586.7  796.88   609.7   806.4
   626.2  810.12   632.6  813.78   639.3  819.59   642.6  820.99   661.1  820.31
#Mann= 7 ,-1,0
       0      .1       0     130     .05       0     150      .1       0
   240.7     .05       0  381.66    .045       0  404.56     .05       0
   440.7      .1       0
#XS Ineff= 2 , 0
                          428.68          788.99
Permanent Ineff=
       F       F
Bank Sta=381.66,404.56
XS Rating Curve= 0 ,0
Exp/Cntr(USF)=0,0
Exp/Cntr=0.3,0.1

Type RM Length L Ch R = 1 ,460     ,109.4,109.5,109.9
XS GIS Cut Line= 6
1658335.35814554459515.5031916661657820.26514754459649.441485143
1657759.58461039459742.6849742361657765.38184904459970.705139693
1657707.26750505  460240.64573871657751.21553821460471.372912756
#Sta/Elev= 30
       0  885.27    50.4  847.04      81  835.52    94.5  827.48   118.2  817.45
   152.1  809.59   192.8   803.7   223.3  795.33   284.3  783.53   348.8  779.39
   668.7  778.68   691.6  777.88   698.2  775.44   704.8  774.13  720.21  775.44
     731  778.51   815.4  779.13  1092.1  775.35  1157.4  780.53  1170.7  785.96
  1196.7  790.84  1214.1  802.34  1237.5  804.56  1247.5  811.33  1274.3   820.2
    1291  828.36  1315.4  849.16  1362.2  899.99  1374.5  908.69  1382.6  911.57
#Mann= 6 ,-1,0
       0      .1       0     180     .05       0   698.2    .045       0
  720.21     .05       0  991.57     .06       0 1297.69      .1       0
#XS Ineff= 2 , 0
                          865.12          797.45
Permanent Ineff=
       F       F
Bank Sta=698.2,720.21
XS Rating Curve= 0 ,0
Exp/Cntr(USF)=0,0
Exp/Cntr=0.3,0.1

Type RM Length L Ch R = 1 ,351     ,,,
XS GIS Cut Line= 4
1658339.27866247459394.6438853141657739.63441231459486.115042117
1657649.85716582459721.5685753711657680.34755142460485.522125711
#Sta/Elev= 30
       0  891.12    26.8  876.35    69.9  844.46    99.8  836.31   126.4  825.59
   152.9  818.69   179.5  815.32   292.3   792.1   341.9  784.12   511.3   779.6
   600.9  780.62     708  778.02   830.4   780.5   859.1  776.55   937.7   776.6
  948.43  774.69     964  773.08     976  774.68   983.7  778.85   990.3  779.25
  1387.6  775.41    1404  780.99    1427  782.71  1463.1  797.61  1489.4  798.16
  1509.1  810.85  1525.5  812.27  1545.2  819.89  1561.6  831.751623.131  891.37
#Mann= 8 ,-1,0
       0      .1       0     210     .05       0  836.58      .1       0
  948.43    .045       0     976      .1       0 1048.57     .05       0
 1258.57     .06       0 1558.57      .1       0
#XS Ineff= 2 , 0
                         1126.25          800.96
Permanent Ineff=
       F       F
Bank Sta=948.43,976
XS Rating Curve= 0 ,0
Exp/Cntr(USF)=0,0
Exp/Cntr=0.3,0.1
LCMann Table=0

Chan Stop Cuts=-1
Use User Specified Reach Order=0
Composite Channel Slope=5